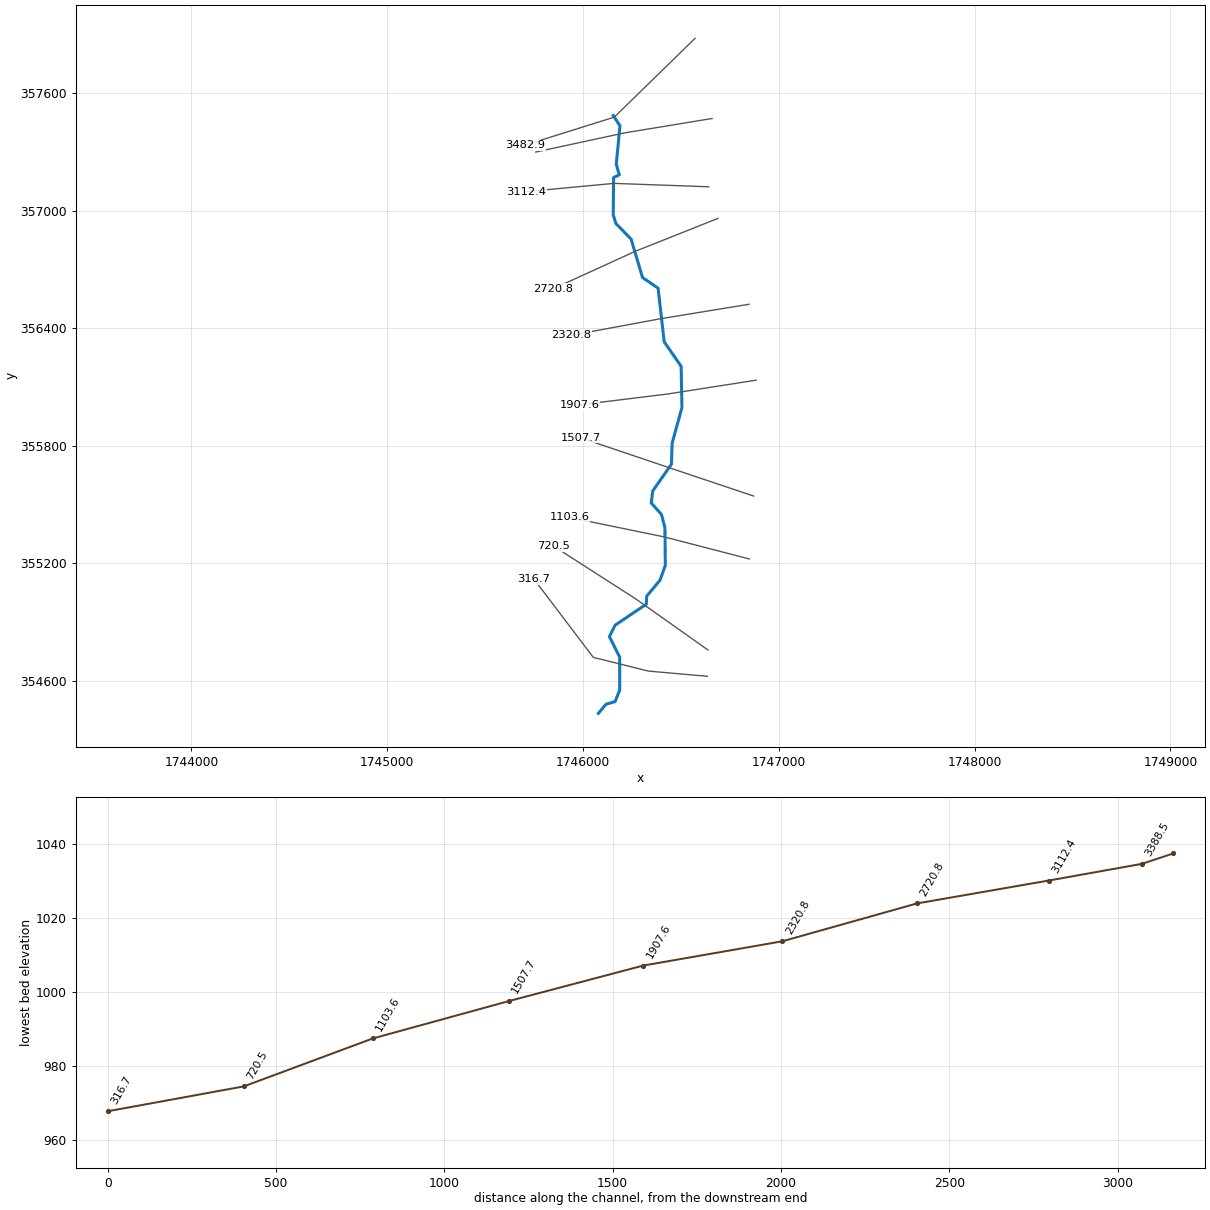
--- PrrshRn.prj (project) ---

Proj Title=PrrshRn
Current Plan=p01
Geom File=g01
Flow File=f01
Plan File=p01
DSS Export Rating Curves=0
DSS Export Rating Curve Sorted=0
DSS Export Volume Flow Curves=0
DXF OffsetX=0
DXF OffsetY=0
DXF ScaleX=0
DXF ScaleY=0

--- PrrshRn.p01 (plan) ---

Plan Title=Floodplain
Program Version=4.00
Geom File=g01
Flow File=f01
K Sum by GR=0
Std Step Tol=0.01
Critical Tol=0.01
Num of Std Step Trials=20
Max Error Tol=0.3
Flow Tol Ratio=0.001
Split Flow NTrial=30
Split Flow Tol=0.02
Split Flow Ratio=0.02
Log Output Level=0
Friction Slope Method=1
Unsteady Friction Slope Method=2
Unsteady Bridges Friction Slope Method=1
Global Log Level=0
CheckData=False
Run HTab=0
Run UNet=0
Run PostProcess=0
UNET Theta=0
UNET Theta Warmup=0
UNET ZTol=0
UNET ZSATol=0
UNET MxIter=0
UNET MaxInSteps=0
UNET DtIC=0
UNET DtMin=0
UNET MaxCRTS=0
UNET WFStab=0
UNET SFStab=0
UNET WFX=0
UNET SFX=0
UNET DSS MLevel=0
UNET DZMax Abort=0
UNET Convert EG Bridges=0
UNET Use Existing IB Tables=0
UNET Froude Limit=0
UNET Froude Power=0
Write IC File=0
Echo Input=False
Echo Output=False
Write Detailed=0

--- PrrshRn.f01 (steady flow) ---

Flow Title=NFF Regression Equation
Program Version=4.00
Number of Profiles=1
Profile Names=P100yr
River Rch & RM=PrrshRn,Main      ,3482.9
695.9454
River Rch & RM=PrrshRn,Main      ,3112.4
739.0180
River Rch & RM=PrrshRn,Main      ,2320.8
776.3647
River Rch & RM=PrrshRn,Main      ,316.7
851.4480
Boundary for River Rch & Prof#=PrrshRn,Main      ,1
Up Type=0
Dn Type=3
Dn Slope=0.024399

--- PrrshRn.g01 (geometry) ---

Geom Title=USGS 3m DEM
Program Version=4.00

River Reach=PrrshRn     ,Main
Reach XY= 30
     1746154.458      357487.116     1746188.980      357434.643
     1746169.997      357238.503     1746185.535      357184.119
     1746156.401      357170.523     1746154.458      356980.178
     1746168.054      356935.505     1746245.746      356855.871
     1746304.015      356659.700     1746383.649      356605.316
     1746414.726      356331.452     1746501.358      356206.154
     1746505.509      355995.504     1746455.514      355814.803
     1746451.629      355706.034     1746356.457      355570.074
     1746348.688      355507.921     1746401.130      355449.652
     1746418.610      355381.671     1746420.553      355189.385
     1746393.360      355113.635     1746325.380      355032.059
     1746323.438      354991.271     1746164.170      354884.445
     1746135.035      354826.176     1746187.478      354721.292
     1746187.478      354552.313     1746164.170      354494.044
     1746117.555      354480.448     1746078.709      354433.833

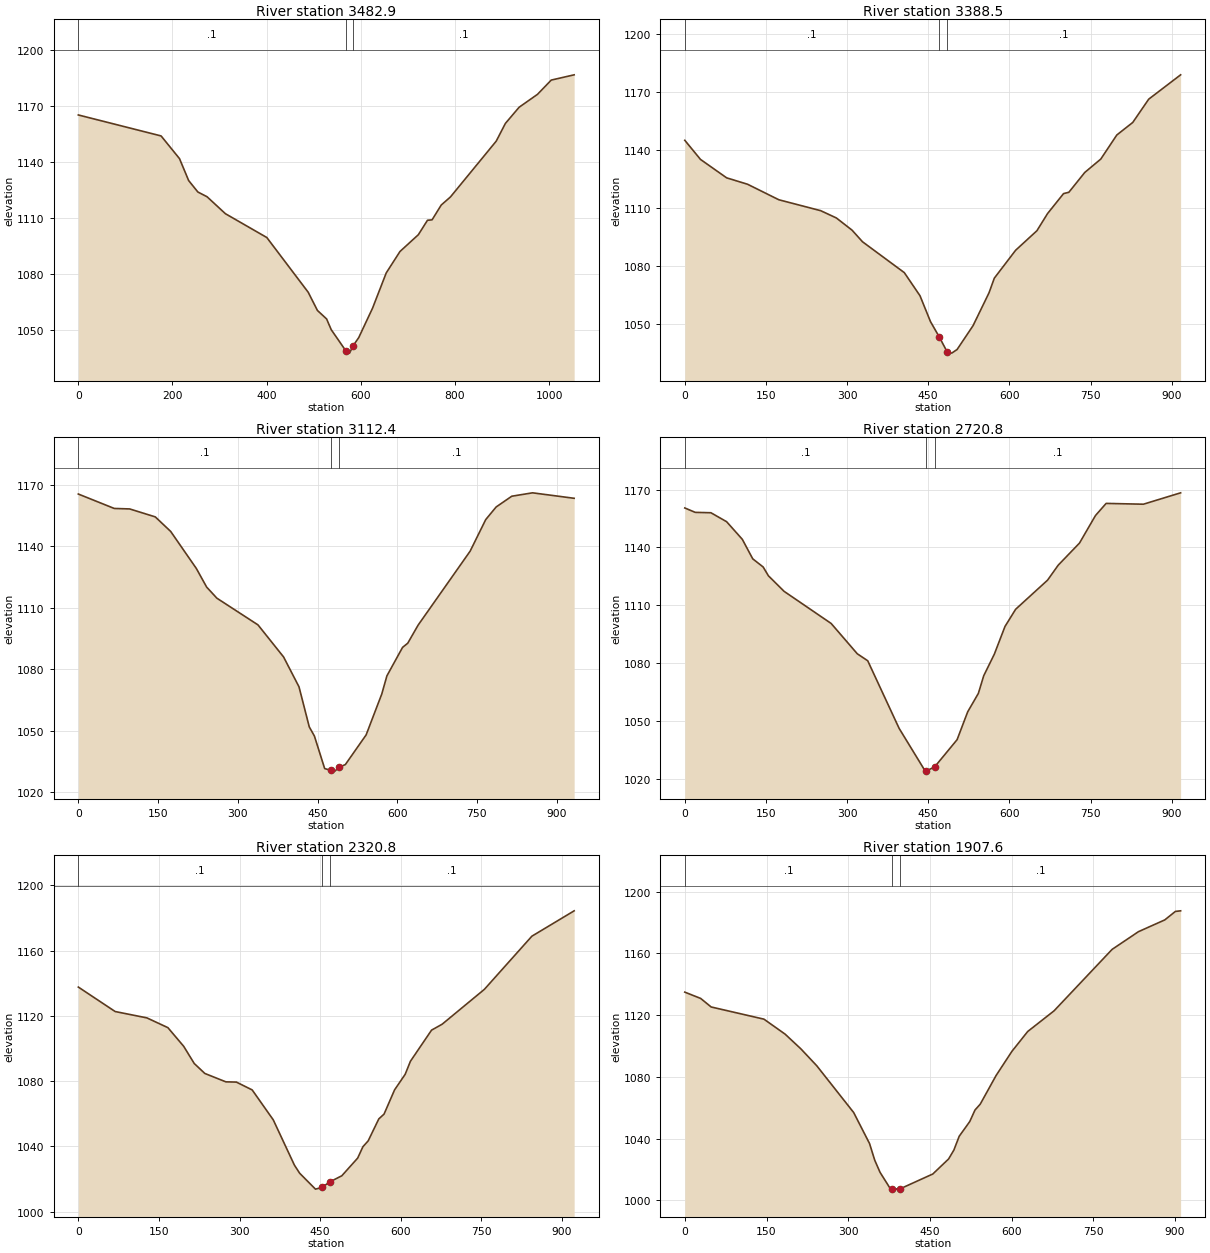
Type RM Length L Ch R = 1 ,3482.9,107.336,94.39,92.22
XS GIS Cut Line= 3
     1746572.441      357881.144     1746159.954      357478.762
     1745704.829      357335.903
#Sta/Elev= 30
       0 1165.05   175.8 1153.82   214.9 1141.68   234.4 1129.92   253.9 1123.81
   273.5 1121.25   312.5 1112.17   400.4 1099.43   488.3 1070.14   507.9 1060.38
   527.4 1055.84   537.2 1050.10   568.7 1038.62   576.2 1037.53   583.7 1041.45
   595.7 1045.86   624.9 1061.53   654.1 1080.48   683.3 1091.95   722.3 1100.93
   741.7 1108.67   751.5 1108.90   770.9 1116.82   790.4 1121.12   887.8 1151.05
   907.2 1160.51   936.4 1169.18   975.4 1176.09  1004.6 1183.72  1053.3 1186.54
#Mann= 3 , 0 , 0
       0     0.1       0   568.7   0.045       0   583.7     0.1       0
Bank Sta=   568.7,   583.7
Exp/Cntr=0.3,0.1

Type RM Length L Ch R = 1 ,3388.5,280.873,276.051,269.071
XS GIS Cut Line= 3
     1746659.360      357471.794     1746211.225      357398.067
     1745759.141      357300.610
#Sta/Elev= 30
       0 1145.05    29.0 1135.14    77.3 1125.59   116.0 1122.26   173.9 1114.21
   251.2 1108.56   280.2 1104.78   309.2 1098.45   328.5 1092.44   405.8 1076.43
   434.8 1064.45   454.2 1051.03   470.3 1043.14   485.3 1035.18   493.5 1034.69
   503.4 1036.57   532.9 1048.94   562.4 1065.97   572.2 1073.57   611.6 1088.03
   651.0 1098.18   670.6 1107.05   700.2 1117.41   710.0 1118.10   739.5 1128.40
   769.0 1135.31   798.6 1147.79   828.1 1154.30   857.6 1166.37   916.6 1179.00
#Mann= 3 , 0 , 0
       0     0.1       0   470.3   0.045       0   485.3     0.1       0
Bank Sta=   470.3,   485.3
Exp/Cntr=0.3,0.1

Type RM Length L Ch R = 1 ,3112.4,381.404,391.61,400.001
XS GIS Cut Line= 3
     1746641.700      357123.077     1746159.221      357140.445
     1745711.090      357098.434
#Sta/Elev= 30
       0 1165.40    67.6 1158.36    96.6 1158.13   144.8 1154.25   173.8 1147.14
   222.1 1129.06   241.4 1120.01   260.7 1114.58   338.0 1101.56   386.2 1085.90
   415.2 1071.33   434.5 1051.80   444.2 1047.31   463.5 1031.45   475.3 1030.55
   482.8 1030.20   490.3 1032.07   502.4 1033.40   541.5 1047.88   570.9 1067.80
   580.6 1076.69   610.0 1090.56   619.8 1092.61   639.3 1101.43   737.2 1137.53
   766.5 1152.92   786.1 1159.08   815.5 1164.33   854.6 1165.99   932.9 1163.32
#Mann= 3 , 0 , 0
       0     0.1       0   475.3   0.045       0   490.3     0.1       0
Bank Sta=   475.3,   490.3
Exp/Cntr=0.3,0.1

Type RM Length L Ch R = 1 ,2720.8,401.207,400,394.505
XS GIS Cut Line= 3
     1746689.453      356961.693     1746267.507      356793.698
     1745846.786      356601.677
#Sta/Elev= 30
       0 1160.47    19.3 1158.19    48.3 1157.99    77.3 1153.35   106.3 1144.22
   125.6 1134.10   144.9 1129.85   154.6 1125.29   183.6 1117.23   270.6 1100.57
   318.9 1084.85   338.2 1081.23   396.2 1046.19   444.5 1024.01   446.7 1024.16
   461.7 1026.14   503.4 1040.32   523.0 1054.77   542.7 1064.32   552.6 1073.46
   572.2 1084.65   591.9 1099.01   611.6 1107.94   670.6 1123.03   690.3 1130.80
   729.7 1142.28   759.2 1156.55   778.9 1162.83   847.8 1162.42   916.6 1168.32
#Mann= 3 , 0 , 0
       0     0.1       0   446.7   0.045       0   461.7     0.1       0
Bank Sta=   446.7,   461.7
Exp/Cntr=0.3,0.1

Type RM Length L Ch R = 1 ,2320.8,413.759,413.231,412.202
XS GIS Cut Line= 3
     1746848.217      356523.102     1746393.360      356448.744
     1745939.263      356364.392
#Sta/Elev= 30
       0 1137.64    68.6 1122.64   127.5 1118.76   166.7 1112.77   196.1 1101.33
   215.7 1090.80   235.4 1084.69   274.6 1079.54   294.2 1079.39   323.6 1074.58
   362.8 1056.24   402.1 1028.54   411.9 1023.53   441.3 1013.78   453.4 1014.78
   468.4 1018.28   490.4 1021.97   519.9 1032.81   529.7 1039.79   539.5 1043.39
   559.2 1056.82   569.0 1059.77   588.6 1074.64   608.3 1084.16   618.1 1092.17
   657.4 1111.24   677.1 1114.87   755.7 1136.24   844.1 1168.82   922.8 1184.38
#Mann= 3 , 0 , 0
       0     0.1       0   453.4   0.045       0   468.4     0.1       0
Bank Sta=   453.4,   468.4
Exp/Cntr=0.3,0.1

Type RM Length L Ch R = 1 ,1907.6,410.783,399.908,388.963
XS GIS Cut Line= 3
     1746884.438      356135.461     1746434.613      356065.074
     1745983.066      356009.555
#Sta/Elev= 30
       0 1134.94    29.1 1130.87    48.4 1125.32   145.3 1117.42   184.1 1107.72
   213.1 1098.16   242.2 1087.23   310.0 1056.89   339.1 1036.81   348.7 1025.96
   358.4 1018.12   377.8 1007.22   380.9 1007.22   395.9 1007.52   455.3 1017.03
   484.3 1026.79   494.0 1032.57   503.7 1041.47   523.1 1051.03   532.7 1058.49
   542.4 1062.35   571.5 1080.91   600.5 1096.56   629.5 1109.42   677.9 1122.83
   784.4 1162.65   832.8 1174.14   881.2 1181.79   900.6 1187.27   910.2 1187.66
#Mann= 3 , 0 , 0
       0     0.1       0   380.9   0.045       0   395.9     0.1       0
Bank Sta=   380.9,   395.9
Exp/Cntr=0.3,0.1

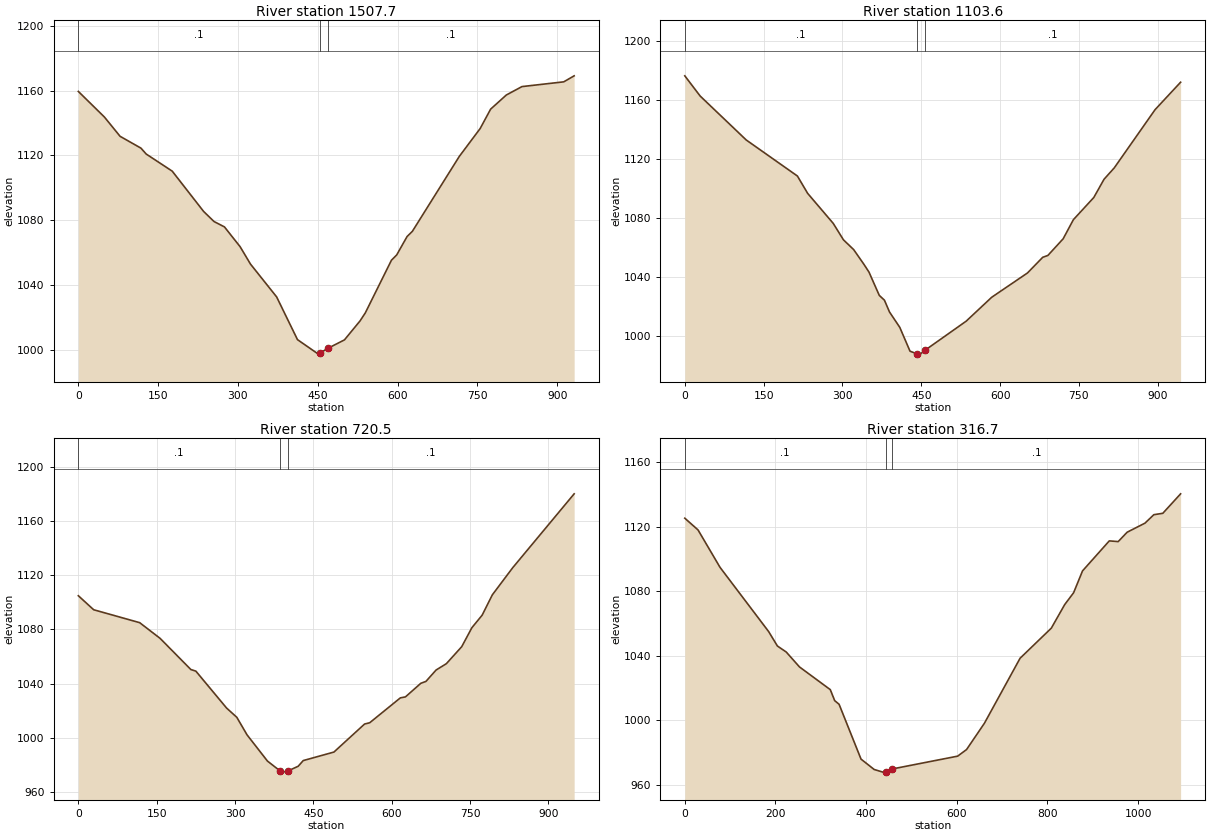
Type RM Length L Ch R = 1 ,1507.7,403.009,404.118,406.354
XS GIS Cut Line= 3
     1746871.776      355543.634     1746434.756      355690.215
     1745988.579      355841.057
#Sta/Elev= 30
       0 1159.45    49.0 1143.68    78.5 1131.79   117.7 1124.51   127.5 1120.89
   176.5 1110.33   235.4 1085.54   255.0 1079.31   274.6 1075.99   304.0 1063.83
   323.6 1053.07   372.7 1032.87   411.9 1006.54   451.1  997.61   453.4  998.12
   468.4 1001.08   500.2 1006.39   529.6 1018.13   539.4 1023.03   588.5 1055.46
   598.3 1058.69   617.9 1070.06   627.8 1073.25   716.1 1119.45   755.3 1136.62
   774.9 1148.53   804.4 1157.24   833.8 1162.43   912.3 1165.35   931.9 1169.06
#Mann= 3 , 0 , 0
       0     0.1       0   453.4   0.045       0   468.4     0.1       0
Bank Sta=   453.4,   468.4
Exp/Cntr=0.3,0.1

Type RM Length L Ch R = 1 ,1103.6,391.874,383.106,373.28
XS GIS Cut Line= 3
     1746849.529      355222.450     1746415.798      355334.814
     1745930.395      355434.589
#Sta/Elev= 30
       0 1176.40    29.2 1162.70   116.9 1132.86   214.3 1108.40   233.8 1096.63
   282.5 1076.24   301.9 1065.10   321.4 1058.45   340.9 1048.46   350.6 1043.14
   370.1 1027.39   379.9 1024.13   389.6 1016.09   409.1 1005.71   428.6  989.51
   442.5  987.60   448.0  987.51   457.5  990.22   535.5 1009.88   584.1 1026.11
   652.1 1042.58   681.2 1053.23   691.0 1054.49   720.1 1065.81   739.5 1078.76
   778.4 1093.83   797.8 1106.17   817.3 1113.92   895.0 1153.44   943.6 1172.07
#Mann= 3 , 0 , 0
       0     0.1       0   442.5   0.045       0   457.5     0.1       0
Bank Sta=   442.5,   457.5
Exp/Cntr=0.3,0.1

Type RM Length L Ch R = 1 ,720.5,393.162,403.785,413.803
XS GIS Cut Line= 3
     1746638.407      354757.450     1746270.871      355017.587
     1745851.001      355287.397
#Sta/Elev= 30
       0 1104.87    29.4 1094.51   117.5 1084.97   156.6 1073.37   215.4 1050.38
   225.1 1049.15   283.9 1021.89   303.5 1015.05   323.0 1002.12   362.2  982.71
   386.4  975.43   391.5  974.56   401.4  975.43   420.9  978.88   430.7  983.10
   489.4  989.38   548.1 1010.09   557.9 1011.03   616.6 1029.41   626.4 1030.15
   655.8 1040.18   665.6 1041.58   685.1 1050.01   704.7 1054.67   734.1 1067.22
   753.6 1081.27   773.2 1090.50   792.8 1105.56   831.9 1125.64   949.4 1180.15
#Mann= 3 , 0 , 0
       0     0.1       0   386.4   0.045       0   401.4     0.1       0
Bank Sta=   386.4,   401.4
Exp/Cntr=0.3,0.1

Type RM Length L Ch R = 1 ,316.7,337.086,316.691,293.821
XS GIS Cut Line= 4
     1746635.143      354623.254     1746334.661      354649.741
     1746052.731      354719.864     1745749.553      355119.670
#Sta/Elev= 30
       0 1125.33    29.2 1118.05    77.8 1094.82   184.9 1055.05   204.3 1046.07
   223.8 1042.34   253.0 1033.09   321.0 1019.00   330.7 1012.18   340.4 1009.93
   388.8  975.92   417.9  969.47   437.2  967.85   442.8  968.05   457.8  969.82
   602.0  977.76   621.7  981.87   661.0  998.15   739.7 1038.47   808.6 1057.13
   838.1 1071.73   857.8 1079.09   877.5 1092.65   936.5 1111.25   956.2 1110.82
   975.9 1116.63  1015.2 1122.25  1034.9 1127.51  1054.6 1128.36  1093.9 1140.44
#Mann= 3 , 0 , 0
       0     0.1       0   442.8   0.045       0   457.8     0.1       0
Bank Sta=   442.8,   457.8
Exp/Cntr=0.3,0.1